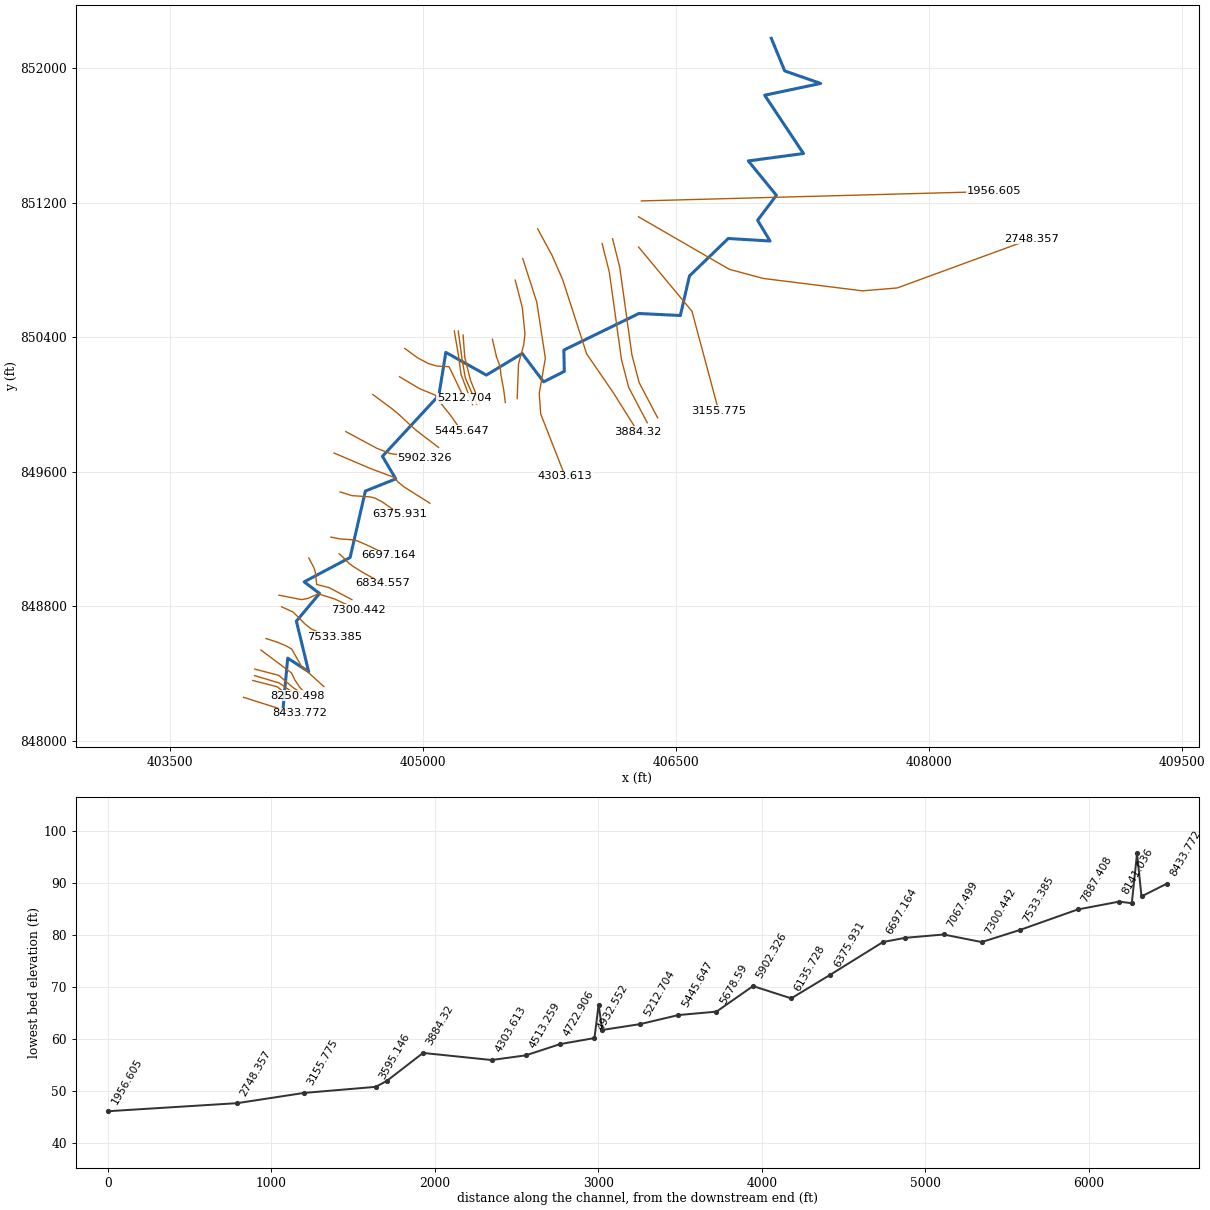
--- 7599_ras.prj (project) ---

Proj Title=7599
Current Plan=p01
Default Exp/Contr=0.3,0.1
English Units
Geom File=g01
Flow File=f01
Plan File=p01
Y Axis Title=Elevation
X Axis Title(PF)=Main Channel Distance
X Axis Title(XS)=Station
BEGIN DESCRIPTION:
RFD model 7599 exported to HEC-RAS
END DESCRIPTION:

--- 7599_ras.p01 (plan) ---

Plan Title=Plan 01
Program Version=4.10
Short Identifier=Plan 01
Geom File=g01
Flow File=f01
Subcritical Flow
Calc Critical at every XS
Secant Critical Depth

--- 7599_ras.f01 (steady flow) ---

Flow Title=Flow 01
Program Version=5.01
Number of Profiles= 6
Profile Names=10yr,25yr,50yr,100yr,100plus,500yr
River Rch & RM=7599,33,8433.772
  555.67  874.31 1168.64 1429.63 2087.26 3004.42
River Rch & RM=7599,33,8277.794
  558.69  879.12 1175.14 1437.65 2098.97 3019.17
River Rch & RM=7599,33,8250.498
  560.36  881.79 1178.75  1442.1 2105.47 3027.36
River Rch & RM=7599,33,8141.036
  562.03  884.46 1182.36 1446.55 2111.97 3035.53
River Rch & RM=7599,33,7533.385
  565.37   889.8 1189.57 1455.44 2124.94 3051.85
River Rch & RM=7599,33,7300.442
  575.04  905.24 1210.42 1481.16 2162.49 3098.99
River Rch & RM=7599,33,7067.499
  576.37  907.36 1213.29  1484.7 2167.66 3105.47
River Rch & RM=7599,33,6834.557
   577.7  909.49 1216.16 1488.24 2172.83 3111.94
River Rch & RM=7599,33,6697.164
  578.03  910.02 1216.88 1489.12 2174.12 3113.56
River Rch & RM=7599,33,6375.931
  588.65  926.97 1239.78 1517.37 2215.36 3165.16
River Rch & RM=7599,33,6135.728
   593.6  934.89 1250.48 1530.57 2234.63 3189.23
River Rch & RM=7599,33,5902.326
  673.22 1062.19 1422.58 1742.92 2544.66 3572.97
River Rch & RM=7599,33, 5678.59
  677.65  1069.3 1432.22 1754.83 2562.05  3594.4
River Rch & RM=7599,33,5445.647
  678.91 1071.33 1434.97 1758.23 2567.02 3600.51
River Rch & RM=7599,33,5212.704
  681.44 1075.39 1440.46 1765.03 2576.94 3612.72
River Rch & RM=7599,33,4979.761
  682.39 1076.91 1442.52 1767.57 2580.66  3617.3
River Rch & RM=7599,33,4932.552
  683.97 1079.44 1445.96 1771.82 2586.86 3624.92
River Rch & RM=7599,33,4722.906
   688.7 1087.03 1456.25 1784.54 2605.43 3647.75
River Rch & RM=7599,33,4303.613
  690.59 1090.07 1460.36 1789.62 2612.85 3656.87
River Rch & RM=7599,33, 3884.32
  845.24 1337.09 1794.17 2201.24 3213.81 4378.59
River Rch & RM=7599,33,3663.658
  852.17 1348.22 1809.26 2219.91 3241.06 4411.09
River Rch & RM=7599,33,3595.146
  859.97 1360.76 1826.27 2240.95 3271.79 4447.71
River Rch & RM=7599,33,3155.775
  868.67 1374.73 1845.23  2264.4 3306.02 4488.42
Boundary for River Rch & Prof#=7599,33,1
Up Type= 0
Dn Type= 2
Boundary for River Rch & Prof#=7599,33,2
Up Type= 0
Dn Type= 2
Boundary for River Rch & Prof#=7599,33,2
Up Type= 0
Dn Type= 2
Boundary for River Rch & Prof#=7599,33,2
Up Type= 0
Dn Type= 2
Boundary for River Rch & Prof#=7599,33,2
Up Type= 0
Dn Type= 2
Boundary for River Rch & Prof#=7599,33,2
Up Type= 0
Dn Type= 2

--- 7599_ras.g01 (geometry) ---

Geom Title=7599
Program Version=4.10

River Reach=7599,33
Reach XY= 30
404167.997120023848185.233014524404196.371043891848492.426317886
404320.774897695848411.621903434404247.811934859848711.876533031
404385.311934948848876.807088584404293.950594187848945.763841137
404566.450594187849090.763841137404656.978601545849485.418199688
404837.395268083849557.918199688404758.228601545849692.084866375
405092.811934739850054.168199703405134.061934739850310.001533031
405374.478601396850175.001533031405586.839712501850303.195977479
405714.061934769850134.862644181 405836.83971253850197.084866419
405834.061934739850323.751533031406279.159156978850541.070977524
406524.976246715850529.212050095406579.032999575850764.263107121
406809.032999575850987.040884942407056.810777396850972.040884912
406982.921888441 851095.37421827407094.588555276851243.707551539
406927.921888441851448.151995987 407255.14411068851492.040884927
 407025.14411068851838.707551584407356.810777336851908.707551554
407144.032999575851983.151996031 407064.49302268852176.893357679

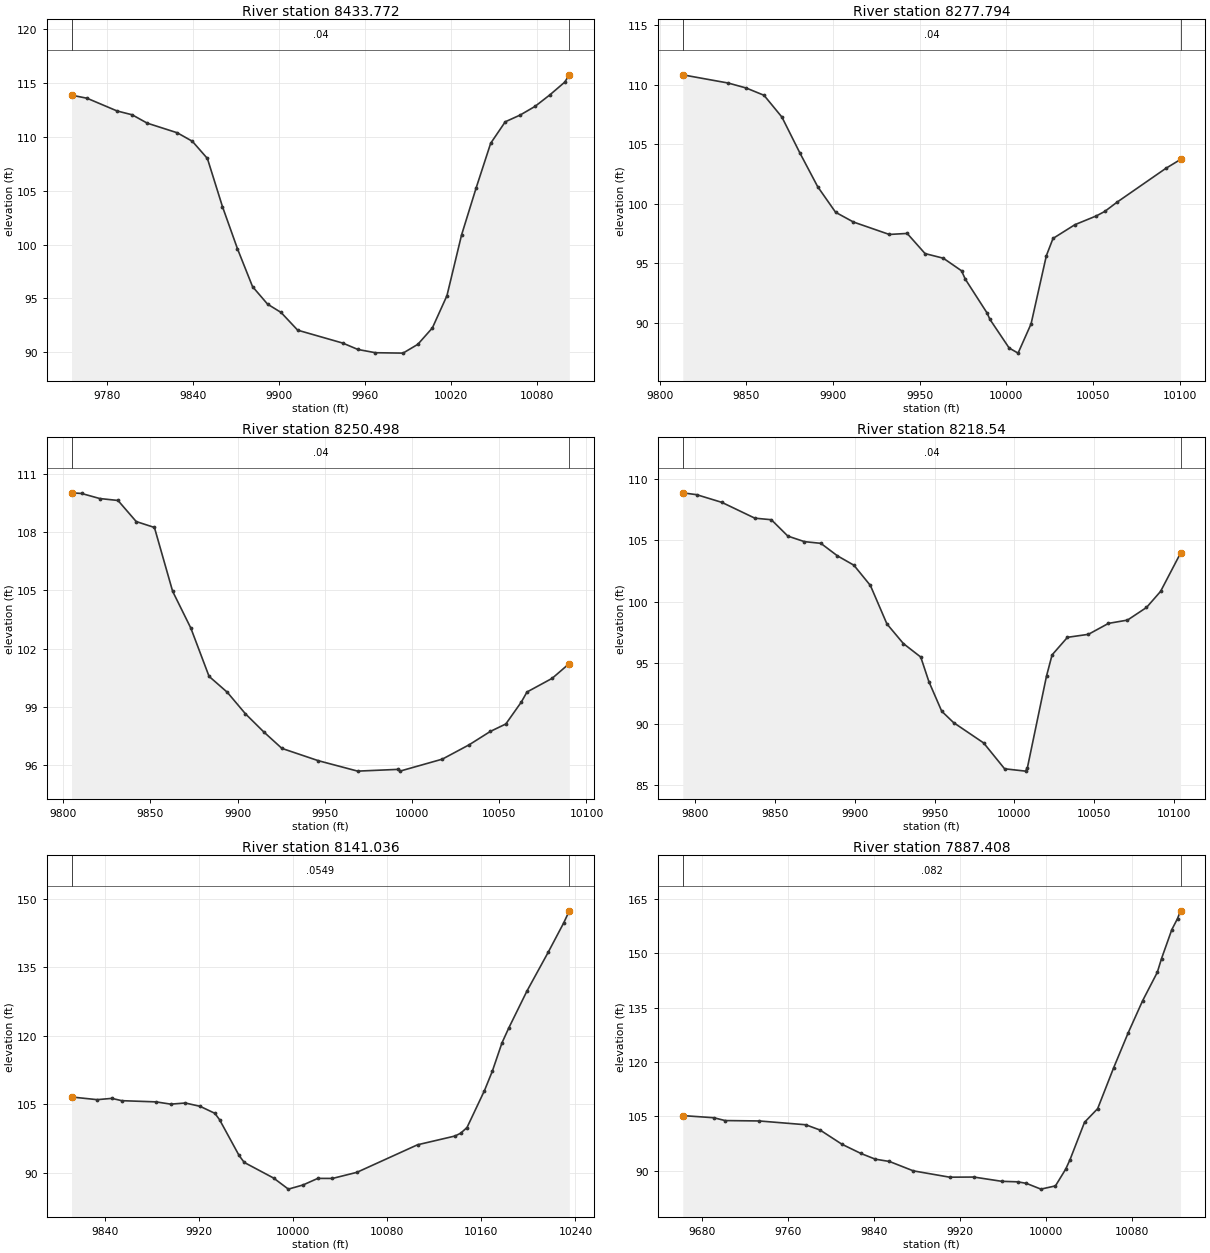
Type RM Length L Ch R = 1 ,8433.772,155.978100,155.978100,155.978100
XS GIS Cut Line= 6
403934.721738309848259.388123453404160.644452482848187.354310334
 404167.20044145848186.401476443404169.165581912848186.029693142
404226.504847318848175.563340724 404268.06851849848163.908494964
#Sta/Elev= 30
9755.247113.87229766.035113.58579787.027112.40269797.523112.04829808.019111.2724
9829.011110.37579839.507109.58759850.003107.99039860.499103.52379870.99599.59954
9881.49196.089579891.98794.461189901.36893.691779912.97992.044159944.46790.84325
9954.96390.252679967.206 89.95089986.45189.912599996.776  90.72910006.9392.25246
 10017.1 95.250410027.26100.874210037.43105.243310047.59109.401210057.76111.3981
10068.11 112.021 10078.5112.824610088.88113.897710099.27115.082810102.45115.7599
#Mann= 3 , 0 , 0
9755.247    0.04       09755.247    0.04       010102.45    0.04       0
#XS Ineff= 2 , 0
       0                               0
Bank Sta=9755.247,10102.45
Exp/Cntr=0.3,0.1

Type RM Length L Ch R = 1 ,8277.794,27.296000,27.296000,27.296000
XS GIS Cut Line= 4
403989.598707944848359.375859991404134.034154788848322.172790334
404197.836238116848272.693623662404245.124800935848240.267180577
#Sta/Elev= 28
 9813.31 110.829 9839.54110.13859849.867 109.7239860.193109.10969870.519107.2783
9880.846104.27429891.172101.42519901.49999.274839911.82598.454619932.47897.41188
9942.80497.497349953.13195.803349963.68295.413459974.16494.358539976.33793.65538
9988.99190.790149990.482 90.289710001.6587.86552 10006.887.43619 10014.389.89638
10023.1295.6272510026.9697.0758910039.6198.2337910051.8998.96552 10056.899.34323
10064.01 100.13510092.17102.977310100.54103.7143
#Mann= 3 , 0 , 0
 9813.31    0.04       0 9813.31    0.04       010100.54    0.04       0
#XS Ineff= 2 , 0
       09950.802        10039.67       0
Bank Sta=9813.31,10100.54
Exp/Cntr=0.3,0.1

Type RM Length L Ch R = 1 ,8250.498,31.958300,31.958300,31.958300
XS GIS Cut Line= 4
403999.494541317848388.542526677404145.158659577848344.880021602
404207.732071459848301.860290349404255.020634264848269.433847249
#Sta/Elev= 25
9804.812110.00979810.559109.97679820.999109.71589831.439 109.6179841.878 108.533
9852.318108.22959862.757104.94769873.197103.05499883.636100.57589894.07699.75837
9904.51698.648999914.95597.723629925.39596.872839946.27496.240639968.82295.70427
 9991.9795.794459993.09395.7048210017.3696.3208210032.8197.0621410044.9497.74843
10053.7598.1272810062.6399.2544410065.8899.7708210080.31100.473810090.15101.2333
#Mann= 3 , 0 , 0
9804.812    0.04       09804.812    0.04       010090.15    0.04       0
#XS Ineff= 2 , 0
       09942.709        10029.17       0
Bank Sta=9804.812,10090.15
Exp/Cntr=0.3,0.1

Type RM Length L Ch R = 1 , 8218.54,77.503800,77.503800,77.503800
XS GIS Cut Line= 4
404001.340564534848427.222460926404143.148738131848389.881123662
404230.388321459848315.662373632404272.912629247848288.217607647
#Sta/Elev= 30
9792.234108.89579800.962108.7431  9816.7108.11669837.382106.82319847.723 106.695
9858.063105.35759868.404104.90459878.745104.76439889.086103.74579899.427102.9763
9909.768101.31679920.10998.17585 9930.4596.563419941.30795.464669946.409 93.4539
9954.43691.035779961.84290.105419980.69488.441169993.82486.3261810006.9586.13489
10008.1486.4300610020.0893.9093710023.5795.6405310033.2197.0781110046.3497.32348
 10058.998.2182310070.81 98.487410082.7199.5186910091.52 100.83110104.03103.9594
#Mann= 3 , 0 , 0
9792.234    0.04       09792.234    0.04       010104.03    0.04       0
#XS Ineff= 2 , 0
       09937.984        10031.17       0
Bank Sta=9792.234,10104.03
Exp/Cntr=0.3,0.1

Type RM Length L Ch R = 1 ,8141.036,253.628400,253.628400,253.628400
XS GIS Cut Line= 6
404037.586321652848540.638123438404219.416377306 848403.93702358
404238.477056354848362.660382733 404268.16227442848318.527663857
404297.015138447848286.731768072404338.679044485848251.945522696
#Sta/Elev= 30
9811.369106.59789833.155106.01219845.666 106.2959854.033105.79169883.198105.5289
9895.709105.0324 9908.22105.27739920.731104.55329933.242103.02889937.239101.6441
 9953.8893.799269958.26392.280779983.28588.856039995.796 86.440310008.31 87.3531
10020.8288.7883510033.3388.7808210054.0690.1122410105.6696.1407810137.5798.06176
10142.3398.6711410147.7499.9093110162.62108.005810169.34112.275610177.51 118.443
10183.21121.658810198.81129.809110216.96138.326610229.99144.674210234.78 147.323
#Mann= 3 , 0 , 0
9811.369  0.0549       09811.369  0.0549       010234.78  0.0549       0
#XS Ineff= 2 , 0
       0                 10038.4       0
Bank Sta=9811.369,10234.78
Exp/Cntr=0.3,0.1

Type RM Length L Ch R = 1 ,7887.408,354.022600,354.022600,354.022600
XS GIS Cut Line= 6
404067.542533159848608.998884529404132.909575999848587.816778556
404186.452070117848565.499435022404220.287127256848546.128665507
404277.534238279848444.639859542404410.997779965848323.112081781
#Sta/Elev= 30
9661.899105.22719690.762104.63769701.274 103.8579732.877103.74989776.213102.7014
9789.625101.23669809.99397.307639827.608  94.7719840.98593.197179854.12392.56325
 9876.2989.972969910.08388.227069932.61288.26241  9958.687.085529973.45386.94496
9981.42986.522919994.95384.9301210008.4885.8252510018.0190.45659   1002293.04994
10035.53103.395110047.72107.143210062.57118.4093 10076.1128.065710089.62136.9967
10103.15144.750910107.13148.580610116.67156.558410121.98159.604710124.79161.7559
#Mann= 3 , 0 , 0
9661.899   0.082       09661.899   0.082       010124.79   0.082       0
#XS Ineff= 2 , 0
       0                               0
Bank Sta=9661.899,10124.79
Exp/Cntr=0.3,0.1

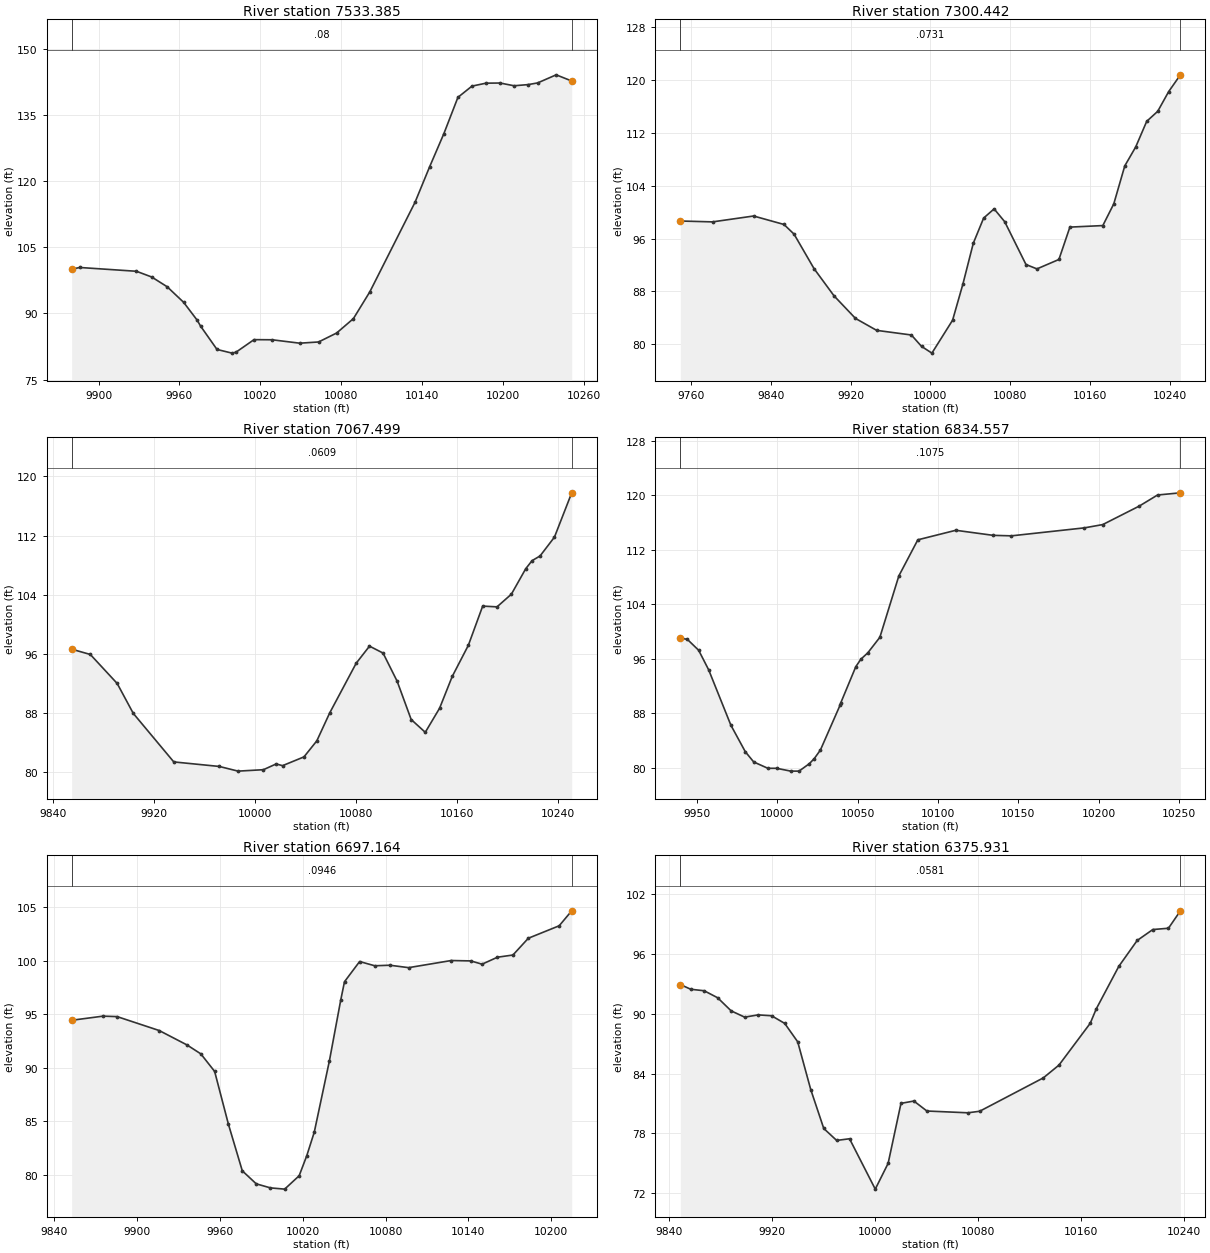
Type RM Length L Ch R = 1 ,7533.385,232.942800,232.942800,232.942800
XS GIS Cut Line= 6
404160.623763263848797.279506624404228.669666618848765.885880962
404298.782438815848695.390786216404334.692002475848666.842330098
404381.098964363848645.391411692404476.076237291848617.998385042
#Sta/Elev= 30
9880.084100.01839886.051100.41169928.10299.551759939.40898.257269950.92796.03339
9963.10292.509459973.16188.450969975.65687.121319987.85281.81595    999980.98333
10001.9481.19553 10015.384.0417610028.6784.0134410049.19 83.237910063.19 83.5159
10076.5485.5406410088.9988.8082910101.1894.8880610134.69 115.19610145.46123.2128
10156.09130.7774 10166.5 139.00710176.91 141.55310187.32142.221910197.72142.2553
10208.13 141.63610218.54141.895410225.62142.278810239.35144.114310250.88142.7146
#Mann= 3 , 0 , 0
9880.084    0.08       09880.084    0.08       010250.88    0.08       0
#XS Ineff= 2 , 0
       0                               0
Bank Sta=9880.084,10250.88
Exp/Cntr=0.3,0.1

Type RM Length L Ch R = 1 ,7300.442,232.942900,232.942900,232.942900
XS GIS Cut Line= 6
404143.991746195848866.759197835404278.801278467848840.082637801
404315.772160927848847.212761144404377.373470928848874.543339085
404473.940780877848844.231122387404615.686258764848778.792244738
#Sta/Elev= 30
9749.19698.657959781.45798.525029822.66999.414449853.18298.133239863.28596.66956
9883.305 91.45799903.39287.334899924.88883.923299946.14282.114249981.00181.41368
9991.15679.6934510001.5878.6700410022.3583.6511910032.7389.1401310043.1295.29435
 10053.599.1037810064.02100.492110074.6698.5465710095.9992.07395   1010791.41428
10129.0392.8387110140.0497.7346610173.0997.96675 10184.1101.258210195.11106.9937
10206.13109.875610217.14113.741710228.16  115.2510239.17118.236310250.94120.7725
#Mann= 3 , 0 , 0
9749.196  0.0731       09749.196  0.0731       010250.94  0.0731       0
#XS Ineff= 2 , 0
       0                10051.72       0
Bank Sta=9749.196,10250.94
Exp/Cntr=0.3,0.1

Type RM Length L Ch R = 1 ,7067.499,232.942800,232.942800,232.942800
XS GIS Cut Line= 6
404321.604429841849087.585358396404352.266651541849028.726694122
404360.465807498849000.930590555404368.342795283848930.134968549
 404441.59120056848911.473199561404577.036899656 848840.10653013
#Sta/Elev= 30
9854.79396.623989869.56795.905369890.82491.98318 9903.5587.937359935.61881.36911
9971.65180.755969986.49680.1231110006.5480.3152210016.6781.0950810021.7280.86185
10038.6782.0486710048.8584.2208610059.0387.9924210079.9894.7150410090.5497.03377
10101.28 96.096510112.4192.2937610123.5387.1081610134.6985.3740410146.0588.64305
10156.0292.9295510168.7797.1399410180.13102.450410191.49102.349710202.85104.0634
10214.21107.508110219.23108.601110225.57109.238210236.94111.782410250.61117.7774
#Mann= 3 , 0 , 0
9854.793  0.0609       09854.793  0.0609       010250.61  0.0609       0
#XS Ineff= 2 , 0
       0                10083.61       0
Bank Sta=9854.793,10250.61
Exp/Cntr=0.3,0.1

Type RM Length L Ch R = 1 ,6834.557,137.392300,137.392300,137.392300
XS GIS Cut Line= 6
404501.675750852849112.460778967404518.721841097849097.675320297
404559.592449218849056.899569005404582.328967273849038.976079822
404646.565509975848998.565115437404757.516221046848938.424883276
#Sta/Elev= 30
9939.60199.059369944.00198.835019950.98797.245049957.23994.361069971.07786.22419
9980.02782.342319985.271 80.83519994.118 79.90129999.47379.9061610008.2979.49175
10013.4979.48861 10019.980.5816510022.9781.3295510026.7982.5868110039.1289.22186
10039.5289.5463910048.8594.8397510052.01 95.934410056.3296.8720210063.8299.15265
10075.64108.173310087.45113.469910111.08114.870110134.34114.127710145.71114.0538
10191.21115.227610202.58115.708210225.33118.427310236.71 120.05410250.94120.3734
#Mann= 3 , 0 , 0
9939.601  0.1075       09939.601  0.1075       010250.94  0.1075       0
#XS Ineff= 2 , 0
       0                10111.56       0
Bank Sta=9939.601,10250.94
Exp/Cntr=0.3,0.1

Type RM Length L Ch R = 1 ,6697.164,321.233700,321.233700,321.233700
XS GIS Cut Line= 6
404452.794281824849211.855993665404504.180600388849201.257820047
 404580.72869183849195.926648907404611.681585116 849188.71153403
404685.832616164849155.775579191404793.116435958849102.498519174
#Sta/Elev= 30
9852.80194.451949875.50594.838489885.70994.794559916.16293.494859936.276 92.1492
9946.28391.31627 9956.2989.676579966.29784.727719976.31580.390799986.43979.17524
9996.70778.7987510006.98 78.682910017.4779.9318810022.9881.8059310028.41 84.0026
10039.3590.6556410047.6196.3708610050.2998.0532510061.2499.9384210072.1899.54272
10083.1299.5927910096.7299.3670210127.54 100.03210141.6899.9964510149.8799.69086
10161.03100.3427 10172.2100.546110183.36102.113910205.69 103.27710214.76104.6737
#Mann= 3 , 0 , 0
9852.801  0.0946       09852.801  0.0946       010214.76  0.0946       0
#XS Ineff= 2 , 0
       0                               0
Bank Sta=9852.801,10214.76
Exp/Cntr=0.3,0.1

Type RM Length L Ch R = 1 ,6375.931,240.202600,240.202600,240.202600
XS GIS Cut Line= 6
404507.354619473 849480.31188301 404576.70988062849458.487118296
404682.812395662849451.167091094404713.193832904849444.171157889
 404755.20602271849422.121853985404862.645380527849347.758604966
#Sta/Elev= 30
 9848.45 92.93829856.49992.466799866.97892.315499877.45691.611059887.93590.29796
9898.41389.669459908.89289.89375 9919.3789.807919929.55689.041659939.68187.19236
9949.80682.403859959.93278.498349969.95477.297739979.96477.465979999.97272.41198
10009.97 74.995510019.9781.01824   1003081.2506710040.1180.2499510072.0180.07047
10081.1580.2257210130.6283.5724710142.7884.85491 10167.1 89.051310171.7790.49308
10189.3494.7694810203.5997.3601910215.75 98.457910227.9198.5877610237.21100.3357
#Mann= 3 , 0 , 0
 9848.45  0.0581       0 9848.45  0.0581       010237.21  0.0581       0
#XS Ineff= 2 , 0
       0                10033.05       0
Bank Sta=9848.45,10237.21
Exp/Cntr=0.3,0.1

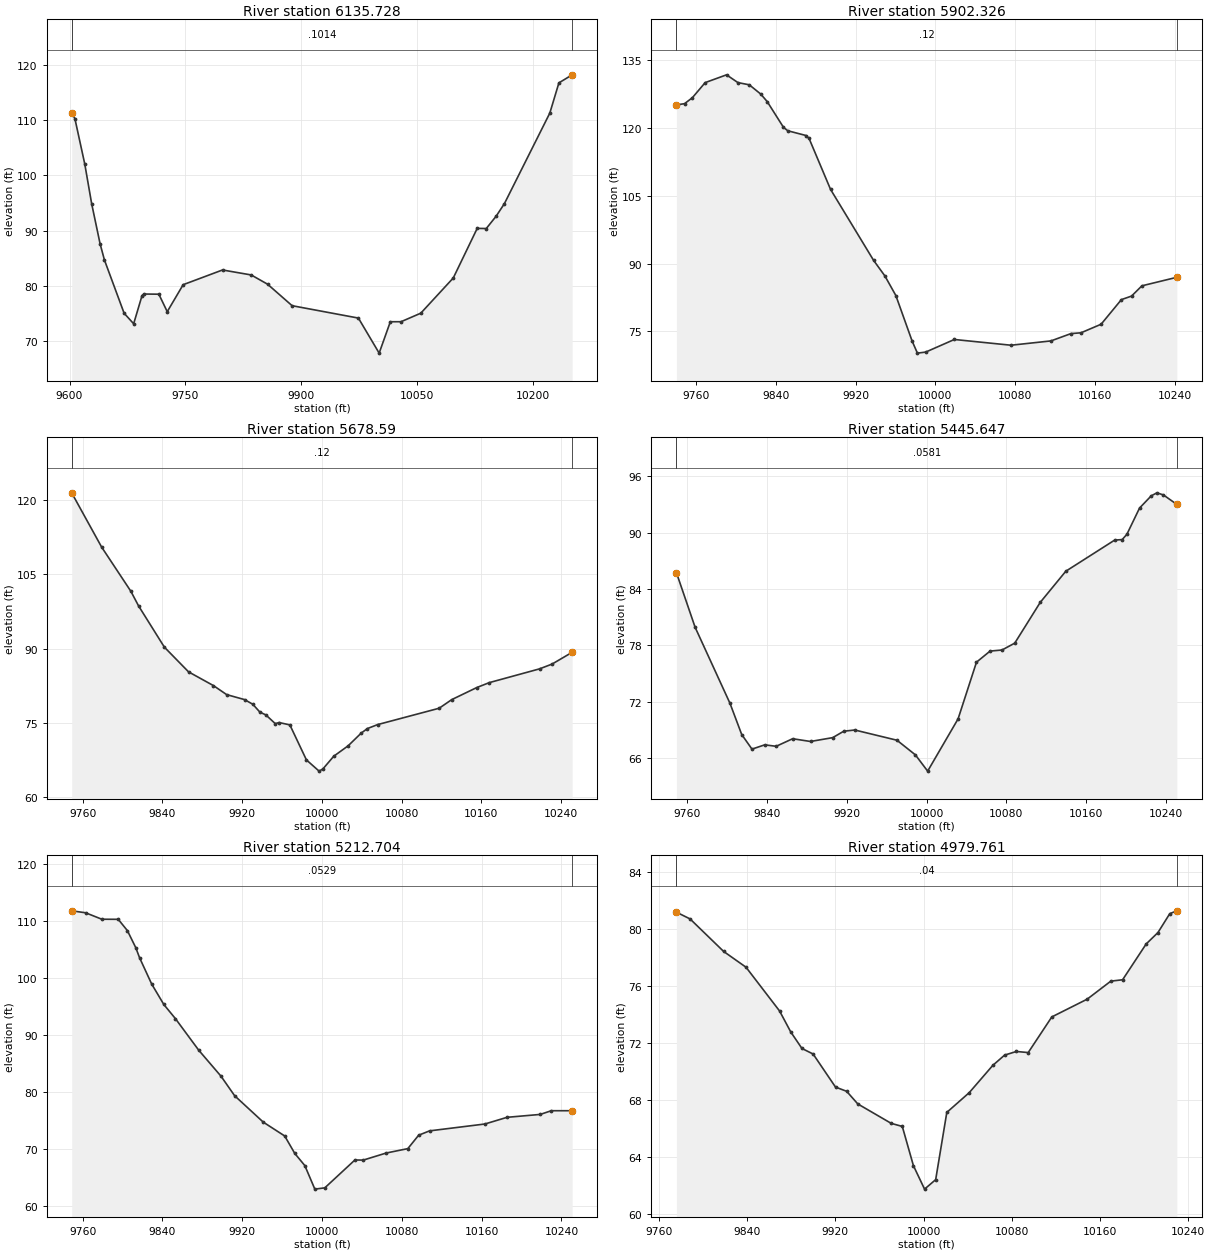
Type RM Length L Ch R = 1 ,6135.728,233.401800,233.401800,233.401800
XS GIS Cut Line= 6
404471.180071622  849711.6450679404687.530437171849619.344623178
404824.906554371849567.749119878404851.392946184849538.398408756
404887.220198542849509.705505922405039.607469827849413.276381046
#Sta/Elev= 30
9602.821111.29089606.974110.22639619.755102.02739628.71894.82545 9639.5987.61136
9645.23984.677379670.72375.055169683.07873.15724 9693.9578.258799696.20678.52911
9715.694 78.49919726.56675.338719747.17480.216059798.142 82.87699835.28681.97729
9856.52380.303259888.26776.421029974.12574.18309   1000167.8492710015.4873.52196
 10029.373.5247710054.9275.06727   1009781.4342510127.9790.3947210139.7290.36473
10152.5492.6028410163.2394.8730310222.01111.230610233.77116.690910250.94 118.143
#Mann= 3 , 0 , 0
9602.821  0.1014       09602.821  0.1014       010250.94  0.1014       0
#XS Ineff= 2 , 0
       09822.913        10063.61       0
Bank Sta=9602.821,10250.94
Exp/Cntr=0.3,0.1

Type RM Length L Ch R = 1 ,5902.326,223.736400,223.736400,223.736400
XS GIS Cut Line= 6
404540.978238647849838.941610905404724.658686231849739.904581355
404802.297005901849709.231871274404826.568028885849704.925474852
 404929.61474268849699.112295473405008.607069817849679.694727038
#Sta/Elev= 30
9740.391125.08089748.554125.34089756.403126.66059769.263130.00039790.662131.7183
9802.081130.00129813.501129.5112 9824.92 127.4749831.392125.8209 9847.76120.1177
9852.101119.3532 9870.45 118.3039873.429117.65499894.985106.39099938.098 90.7222
9949.45687.269529960.42282.947149976.79372.855219982.04670.213669990.34370.44278
10019.0873.2291210075.92 71.959510115.9472.9128210136.0174.5300910146.0674.70658
10166.2376.5978610186.5982.0417110196.7782.8229910207.1585.0898810242.19 86.9742
#Mann= 3 , 0 , 0
9740.391    0.12       09740.391    0.12       010242.19    0.12       0
#XS Ineff= 2 , 0
       09941.657                       0
Bank Sta=9740.391,10242.19
Exp/Cntr=0.3,0.1

Type RM Length L Ch R = 1 , 5678.59,232.942800,232.942800,232.942800
XS GIS Cut Line= 6
404700.633466941850059.726166572404817.314067237849973.081521064
404860.714665039849936.348457698404929.477372255849871.737828377
404961.391868286849843.992409066405091.003275961849744.968357271
#Sta/Elev= 30
9749.015121.3826 9779.06 110.4449808.368101.54369816.05398.610959841.97290.28639
9866.22585.306829891.21582.535229904.43380.721019922.35279.718759930.63578.78553
9937.83177.181249943.73676.637919953.19974.873759957.08675.094169967.85174.61442
9984.44967.562939997.15665.30281   1000165.7509210011.8968.3100210026.2770.40149
10039.4272.9683210045.5873.8784610055.8574.6782910117.5877.9750810130.1679.70798
10155.3382.1467610167.9183.1402310218.2585.9085710230.8486.8772110250.9889.24586
#Mann= 3 , 0 , 0
9749.015    0.12       09749.015    0.12       010250.98    0.12       0
#XS Ineff= 2 , 0
       09951.868                       0
Bank Sta=9749.015,10250.98
Exp/Cntr=0.3,0.1

Type RM Length L Ch R = 1 ,5445.647,232.942900,232.942900,232.942900
XS GIS Cut Line= 6
404859.467349187850164.946469277404978.525178035850094.244785669
405070.393605938850056.176643812405094.588227473850019.935517871
 405164.71218397849932.028264567405226.479346034849843.969654076
#Sta/Elev= 30
9749.16185.745059767.92179.933769802.86271.855999814.656 68.53139824.94166.98096
9837.726 67.4356  9849.267.281279865.73168.085069883.62267.793659905.90468.20187
9916.97368.884539928.01869.012259970.31967.925579988.79366.3695710001.0864.64246
10031.5970.1946310050.0376.2181510063.6677.3988410075.6277.5139910088.4178.24345
10113.9982.5798110139.5885.8841310188.6189.1961610196.12 89.247510200.8289.80775
10213.5392.5989910225.2593.8976410230.9594.2173910237.4793.9919310250.9492.98552
#Mann= 3 , 0 , 0
9749.161  0.0581       09749.161  0.0581       010250.94  0.0581       0
#XS Ineff= 2 , 0
       09930.845                       0
Bank Sta=9749.161,10250.94
Exp/Cntr=0.3,0.1

Type RM Length L Ch R = 1 ,5212.704,232.942800,232.942800,232.942800
XS GIS Cut Line= 6
404890.570689002850333.557436651404966.036435826850278.223998818
405029.541265268850243.884810586405080.143509365850228.713366954
405153.223178632850224.720535898405243.405945733 850036.17017073
#Sta/Elev= 30
9749.084111.81279763.022111.4708 9779.31110.33599795.732110.32219804.919108.3361
9813.272105.35429817.091103.58439829.26398.949449841.43595.355079853.12292.85654
9876.38387.332359898.78482.747049912.40479.326189941.11974.682759962.61572.24842
9972.75869.170319982.79167.045359992.81662.9095510002.8263.1346210032.9568.02741
 10041.4 68.012610064.3169.2506110086.0370.0262610096.89 72.385310107.8173.14628
10163.2974.3533810185.48 75.528210218.7776.0370110229.8776.6877610250.7676.68709
#Mann= 3 , 0 , 0
9749.084  0.0529       09749.084  0.0529       010250.76  0.0529       0
#XS Ineff= 2 , 0
       0                10035.48       0
Bank Sta=9749.084,10250.76
Exp/Cntr=0.3,0.1

Type RM Length L Ch R = 1 ,4979.761,21.792800,21.792800,21.792800
XS GIS Cut Line= 4
 405184.32387951850437.231005371 405209.32387951850290.703227609
405224.554988116850177.693623632405292.431551456849998.998181477
#Sta/Elev= 30
9775.84381.179159788.251 80.70589818.68478.428239838.973 77.32279869.407 74.2566
9879.55172.787269889.69671.63071 9899.8471.240389920.12968.925229930.24368.62879
9940.33367.744419970.60566.384919980.69566.167489990.785 63.418210000.8861.77579
10010.9762.4409410021.0667.15116 10041.468.53451 10062.8 70.448410073.4971.16615
10084.1971.4190410094.8971.3429110116.2873.8403910148.3775.0846410169.7776.34686
10180.4676.4425910201.8678.9534810212.5579.7528610223.2581.0748210229.6781.27307
#Mann= 3 , 0 , 0
9775.843    0.04       09775.843    0.04       010229.67    0.04       0
#XS Ineff= 2 , 0
       09947.379        10032.51       0
Bank Sta=9775.843,10229.67
Exp/Cntr=0.3,0.1

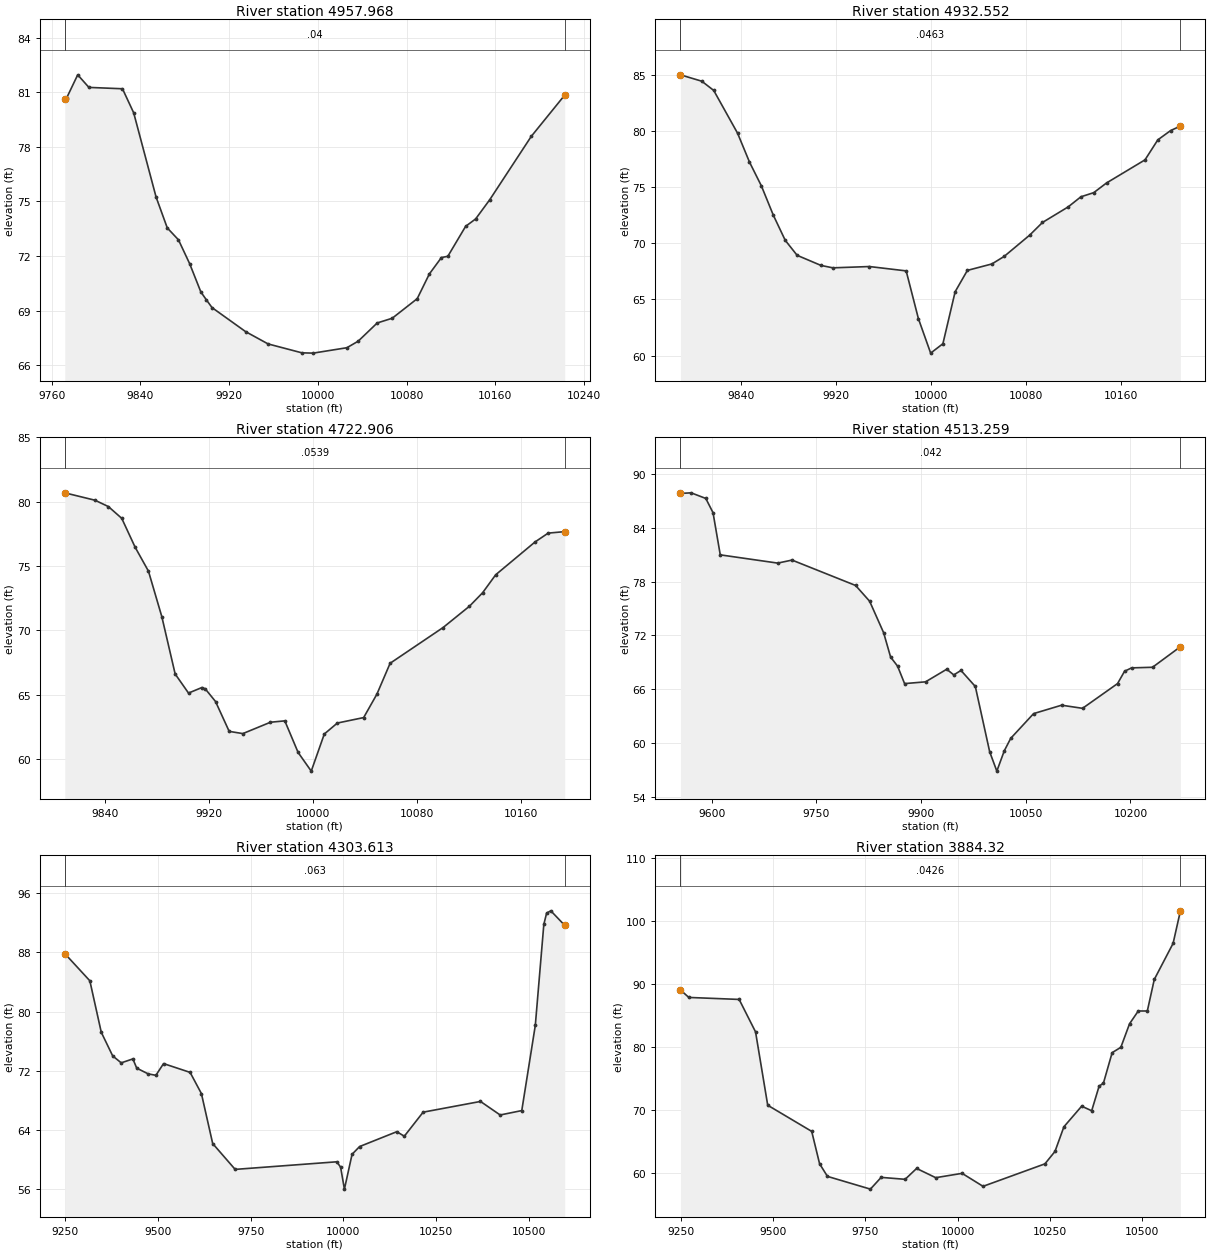
Type RM Length L Ch R = 1 ,4957.968,25.416500,25.416500,25.416500
XS GIS Cut Line= 4
405207.934990644850436.536560953405230.157212853850271.953227624
405249.601657271850158.064338714405317.053003162850003.071442574
#Sta/Elev= 30
9771.86780.611599773.417 80.67129783.50881.959429793.59981.268079823.87181.19287
9833.96279.870549854.14375.242369864.23473.541799874.32572.886429884.41671.57538
9894.50670.021059899.40269.593699904.59769.158849934.86967.837649955.14267.16117
9985.57666.672829995.72166.6563210026.1666.95377 10036.367.3117910053.4868.31466
10067.0168.5746310089.5469.6508310100.4571.0075910111.3571.9115810117.1371.98102
10133.1673.6273610142.1974.0354710154.9875.0982910192.31 78.573110222.5180.84586
#Mann= 3 , 0 , 0
9771.867    0.04       09771.867    0.04       010222.51    0.04       0
#XS Ineff= 2 , 0
       09950.041        10038.75       0
Bank Sta=9771.867,10222.51
Exp/Cntr=0.3,0.1

Type RM Length L Ch R = 1 ,4932.552,209.646300,209.646300,209.646300
XS GIS Cut Line= 4
405236.407212853850412.925449818405246.690404862850279.256123632
405280.851657271850142.786560953405335.712768376850007.369894266
#Sta/Elev= 30
9789.23484.999979807.21384.431069817.24283.609149837.30279.804529847.33177.23523
9857.36175.11119 9867.3972.50653 9877.4270.268199887.44968.930929907.50868.03182
9917.53867.815999948.30367.932019979.22967.544049989.53763.290869999.84660.22279
10010.1561.0592910020.4665.6898110030.7767.5888910051.3968.16239 10061.768.83115
10083.1770.7253910093.96 71.854210115.5473.2371410126.3374.1418110137.1274.50931
10147.9175.3740910180.2877.4294910191.0679.2090110201.8580.0378110210.0980.43764
#Mann= 3 , 0 , 0
9789.234  0.0463       09789.234  0.0463       010210.09  0.0463       0
#XS Ineff= 2 , 0
       09952.047           10041       0
Bank Sta=9789.234,10210.09
Exp/Cntr=0.3,0.1

Type RM Length L Ch R = 1 ,4722.906,209.646300,209.646300,209.646300
XS GIS Cut Line= 6
405410.416182756850387.643331781405434.229366183          850285
405456.206647873850223.476715565405461.051390916850175.783082753
405477.164998949850089.158699304405486.958537221850012.351847038
#Sta/Elev= 30
9809.33280.683869832.57780.108199842.84279.615789853.10878.703789863.37476.46492
9873.63974.600929883.90571.07002 9894.17 66.61399904.43665.130999914.702 65.5616
9917.23765.466329925.19864.476329935.69562.156619946.19261.983579967.43262.86656
9978.45562.972459988.68660.517539998.77559.0686610008.8161.9512510018.84 62.8033
10039.06 63.227910049.2365.04402 10059.467.4450810100.0970.2190110120.39  71.877
10130.4772.9206510140.5574.31903 10170.876.8678410180.88 77.554410193.6377.67012
#Mann= 3 , 0 , 0
9809.332  0.0539       09809.332  0.0539       010193.63  0.0539       0
#XS Ineff= 2 , 0
       09940.528        10037.99       0
Bank Sta=9809.332,10193.63
Exp/Cntr=0.3,0.1

Type RM Length L Ch R = 1 ,4513.259,209.646300,209.646300,209.646300
XS GIS Cut Line= 6
405545.604221016850739.530146554405587.833126515850575.848730013
405603.438679874850418.192570955 405595.95592007850354.653813615
405565.109808475850240.175355792405557.419417322850035.076834142
#Sta/Elev= 30
9555.40287.808779570.71287.874979591.70887.248869602.06585.661669612.42380.97341
9694.73380.055119715.20680.392229806.30877.566319826.40775.809749846.41872.31083
9856.42469.60174 9866.4368.587619876.43666.647249906.50766.843839936.79968.24576
 9946.9467.614599957.21868.112159977.78366.325469998.348 59.0591 10008.656.90834
10019.2959.1752510028.5260.5590910061.2763.3090410101.3664.2442510131.3863.89615
10181.5266.6487610191.5568.0207310201.5868.3965510231.6268.4644210271.5770.75152
#Mann= 3 , 0 , 0
9555.402   0.042       09555.402   0.042       010271.57   0.042       0
#XS Ineff= 2 , 0
       09974.141        10104.08       0
Bank Sta=9555.402,10271.57
Exp/Cntr=0.3,0.1

Type RM Length L Ch R = 1 ,4303.613,419.292600,419.292600,419.292600
XS GIS Cut Line= 6
405590.171530157850867.956892073405673.351240039850609.365774736
405724.399668753850275.293610647405687.979010016850064.740699589
405696.767698616849943.893150434405842.074258327849572.148577362
#Sta/Elev= 30
9249.13387.830139316.65384.155549347.43877.197959378.212 74.00449401.19373.06771
9432.60173.598159442.97372.351129473.95471.574189494.609  71.3849515.26372.96577
9586.81571.777599617.25968.914129647.67362.161569708.18858.670139982.01159.69602
9992.32658.9781310002.6256.0033410023.2660.7110510043.4961.7557910143.8463.76552
   1016463.1511310214.73 66.402610369.2767.8511610422.2866.0221710480.5266.61727
10516.9978.1271210539.9691.7802610547.47 93.304910558.8293.6087810596.3191.63997
#Mann= 3 , 0 , 0
9249.133   0.063       09249.133   0.063       010596.31   0.063       0
#XS Ineff= 2 , 0
       09866.195        10042.69       0
Bank Sta=9249.133,10596.31
Exp/Cntr=0.3,0.1

Type RM Length L Ch R = 1 , 3884.32,220.662600,220.662600,220.662600
XS GIS Cut Line= 6
405678.583327949851044.665298209405764.245537788850886.163347974
405827.496320337850741.106184676405969.165805429850301.268227935
 406126.97314918850070.825843409406272.576079369849838.181043893
#Sta/Elev= 30
9249.03889.034059271.71387.844899408.08987.527539452.52482.367219485.50670.70439
9604.71766.549199626.05761.400529647.39659.392419763.774 57.36719792.93959.23559
9857.87158.927259889.00560.655169940.79459.1866910012.2359.8772810069.0557.81088
10236.7161.3855310264.0563.36621 10288.2  67.28210336.33 70.556110363.4469.82681
10383.5273.7302110395.3174.2237110418.9179.06308 10442.579.91718 10466.183.66092
10489.6985.6901410514.2385.6905810533.0890.7041910584.0796.4394910603.91101.6155
#Mann= 3 , 0 , 0
9249.038  0.0426       09249.038  0.0426       010603.91  0.0426       0
#XS Ineff= 2 , 0
       09856.773        10154.01       0
Bank Sta=9249.038,10603.91
Exp/Cntr=0.3,0.1

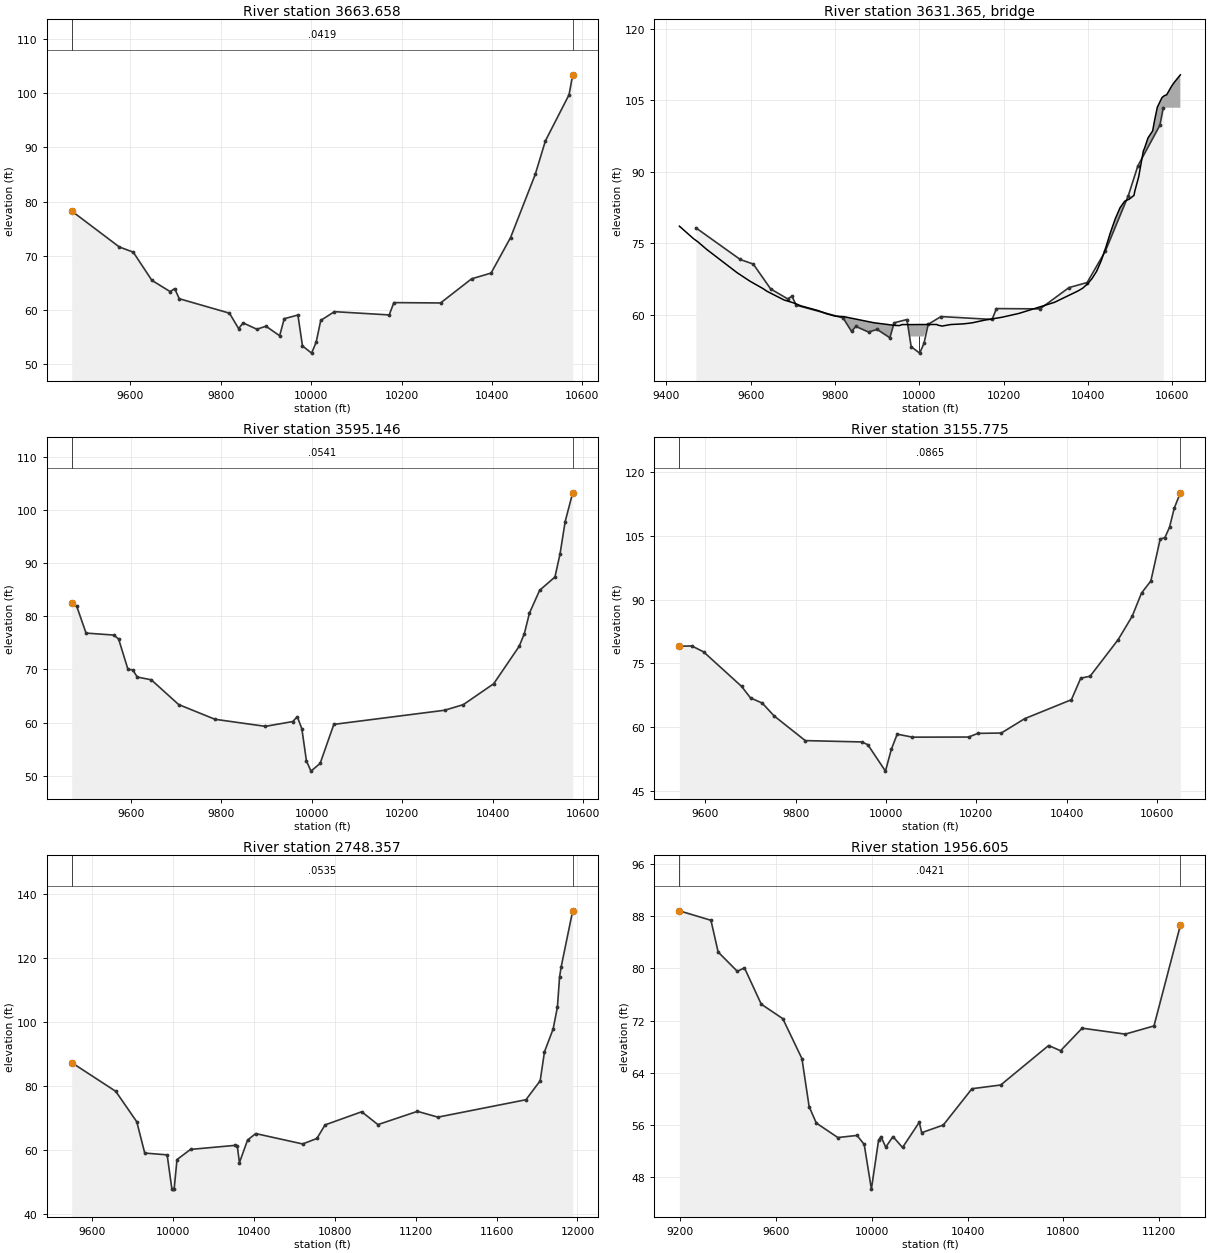
Type RM Length L Ch R = 1 ,3663.658,68.512300,68.512300,68.512300
XS GIS Cut Line= 5
406061.121806572850957.067945379 406103.80848218850786.321242962
406176.047471682850265.872159544 406218.73414729850101.692637983
406328.734426747849891.542850379
#Sta/Elev= 30
9470.19478.260699575.40371.626819606.32670.665069647.52965.459599687.913 63.3775
9698.00963.925999708.10562.062369819.15959.393629839.35156.548549849.44757.59881
9879.73456.421789899.92656.983539930.21455.22256 9940.3158.365989970.59759.04941
9980.693 53.345910000.8852.0121110010.9854.0360810021.0858.0509210051.3659.67231
10172.5459.0689110182.8761.3435710286.19 61.279810354.7865.7363610397.9166.79964
10441.0473.3622710495.5685.0151710518.1391.2318610570.4299.7465410578.47103.4194
#Mann= 3 , 0 , 0
9470.194  0.0419       09470.194  0.0419       010578.47  0.0419       0
#XS Ineff= 2 , 0
       09770.576         10134.2       0
Bank Sta=9470.194,10578.47
Exp/Cntr=0.3,0.1

Type RM Length L Ch R = 3 ,3631.365,,,
BEGIN DESCRIPTION:
END DESCRIPTION:
Bridge Culvert--1,0,-1,-1, 0
Deck Dist Width WeirC Skew NumUp NumDn MinLoCord MaxHiCord MaxSubmerge Is_Ogee
15.699250,37.113800,2.6,0, 60, 60, , , 0.95, 0, 0,0,,
 9431.11 9464.55 9474.87 9495.52 9567.80 9598.44 9628.81 9638.93 9679.42 9699.67
 9719.91 9760.58 9780.65 9800.89 9821.14 9892.00 9942.61 9952.73 9959.06 9976.90
 9976.9010021.8410021.8410041.6010043.8410053.9610074.2010104.5710124.8210155.19
10195.6810236.1710320.6710376.0510387.1310398.2010409.2810420.3510431.4310442.51
10453.5810464.4810475.7310486.8110497.8910508.9610511.0010520.0410531.1110534.26
10542.1910553.2710557.5210564.3410575.4210580.7810586.4910597.5710604.0310618.93
   78.61   75.99   75.33   73.76   68.87   67.08   65.56   64.96   63.14   62.60
   61.90   60.91   60.24   59.75   59.65   58.38   57.81   57.78   57.99   57.99
   57.99   58.01   58.01   58.01   57.88   57.68   58.00   58.14   58.35   58.93
   59.52   60.33   62.66   65.03   65.60   66.47   67.61   69.15   71.40   74.26
   77.41   80.13   82.44   83.83   84.28   85.06   85.97   88.92   94.35   95.01
   97.10   98.58  100.65  103.54  105.55  105.94  106.13  107.85  108.68  110.31
 -921.39 -924.01 -924.67 -926.24 -931.13 -932.92 -934.44 -935.04 -936.86 -937.40
 -938.10 -939.09 -939.76 -940.25 -940.35 -941.62 -942.19 -942.22 -942.01 -942.01
   55.49   55.51 -941.99 -941.99 -942.12 -942.32 -942.00 -941.86 -941.65 -941.07
 -940.48 -939.67 -937.34 -934.97 -934.40 -933.53 -932.39 -930.85 -928.60 -925.74
 -922.59 -919.87 -917.56 -916.17 -915.72 -914.94 -914.03 -911.08 -905.65 -904.99
 -902.90 -901.42 -899.35 -896.46 -894.45 -894.06 -893.87 -892.15 -891.32 -889.69
 9431.11 9464.55 9474.87 9495.52 9567.80 9598.44 9628.81 9638.93 9679.42 9699.67
 9719.91 9760.58 9780.65 9800.89 9821.14 9892.00 9942.61 9952.73 9959.06 9980.52
 9980.5210025.4710025.4710041.6010043.8410053.9610074.2010104.5710124.8210155.19
10195.6810236.1710320.6710376.0510387.1310398.2010409.2810420.3510431.4310442.51
10453.5810464.4810475.7310486.8110497.8910508.9610511.0010520.0410531.1110534.26
10542.1910553.2710557.5210564.3410575.4210580.7810586.4910597.5710604.0310618.93
   78.61   75.99   75.33   73.76   68.87   67.08   65.56   64.96   63.14   62.60
   61.90   60.91   60.24   59.75   59.65   58.38   57.81   57.78   57.99   57.99
   57.99   58.01   58.01   58.01   57.88   57.68   58.00   58.14   58.35   58.93
   59.52   60.33   62.66   65.03   65.60   66.47   67.61   69.15   71.40   74.26
   77.41   80.13   82.44   83.83   84.28   85.06   85.97   88.92   94.35   95.01
   97.10   98.58  100.65  103.54  105.55  105.94  106.13  107.85  108.68  110.31
 -921.39 -924.01 -924.67 -926.24 -931.13 -932.92 -934.44 -935.04 -936.86 -937.40
 -938.10 -939.09 -939.76 -940.25 -940.35 -941.62 -942.19 -942.22 -942.01 -942.01
   55.49   55.51 -941.99 -941.99 -942.12 -942.32 -942.00 -941.86 -941.65 -941.07
 -940.48 -939.67 -937.34 -934.97 -934.40 -933.53 -932.39 -930.85 -928.60 -925.74
 -922.59 -919.87 -917.56 -916.17 -915.72 -914.94 -914.03 -911.08 -905.65 -904.99
 -902.90 -901.42 -899.35 -896.46 -894.45 -894.06 -893.87 -892.15 -891.32 -889.69
Pier Skew, UpSta & Num, DnSta & Num=  ,9999.37, 2 ,10003.00, 2 , 0 , 0 , 0 ,,
    2.00    2.00
 -942.00   58.00
    2.00    2.00
 -942.00   58.00
BR Coef=-1 , 0 , 0 ,, 0 ,,,0.8,0,1,0,
WSPro=,,,, 1 ,,,, 0 ,,,, 0 ,,,,-1 ,-1 ,-1 , 0 , 0 , 0 , 0 , 0
BC Design=,, 0 ,, 0 ,,,,,,

Type RM Length L Ch R = 1 ,3595.146,439.370700,439.370700,439.370700
XS GIS Cut Line= 5
406122.944129398850985.752203707406165.630805006850815.005501289
406237.869794508850294.556417872406280.556470116850130.376896311
406390.556749573849920.227108706
#Sta/Elev= 30
9469.106 82.50179480.189 81.90879500.805 76.85689562.65176.483019572.95975.71576
9593.57570.010569603.88369.93377 9614.1968.575979645.11368.057019705.68963.39233
9785.99260.62023 9897.5159.287289958.08560.190469968.18161.114219978.27758.79905
9988.37352.773129998.46950.8508710018.6652.3034210048.9559.6589210294.0862.32063
10335.4163.3784310402.6967.3190210459.1274.3891110470.4176.75023 10481.780.62145
10504.2784.9216310538.1387.4219110549.4291.7841310560.7197.8690310577.38103.2814
#Mann= 3 , 0 , 0
9469.106  0.0541       09469.106  0.0541       010577.38  0.0541       0
#XS Ineff= 2 , 0
       09788.096        10121.64       0
Bank Sta=9469.106,10577.38
Exp/Cntr=0.3,0.1

Type RM Length L Ch R = 1 ,3155.775,407.417700,407.417700,407.417700
XS GIS Cut Line= 3
406277.051210433850936.261387423406593.891488224 850554.31694296
 406752.31162709849961.869026303
#Sta/Elev= 30
9542.54679.04776 9570.1779.101329596.15677.717059680.29769.600499700.09966.88666
9726.08565.677969752.07162.68498 9821.2656.857319946.96456.538279959.95655.88303
9998.93549.6803310011.9354.8084710024.9258.37178 10058.857.6649910183.0157.69398
10203.7258.5563910255.4758.6341210307.2362.0109210410.7466.4670310431.4471.53131
10452.1571.9883110514.2680.5880510545.3186.0801810566.0191.5393710586.7294.38668
10607.42104.252510617.77104.550910628.12107.032510638.47 111.48810652.06115.0996
#Mann= 3 , 0 , 0
9542.546  0.0865       09542.546  0.0865       010652.06  0.0865       0
#XS Ineff= 2 , 0
       09784.302        10166.72       0
Bank Sta=9542.546,10652.06
Exp/Cntr=0.3,0.1

Type RM Length L Ch R = 1 ,2748.357,791.751800,791.751800,791.751800
XS GIS Cut Line= 6
406276.663289249851116.108320192406815.725789219850803.608320192
 407016.94880259850749.478414446407605.056441486850675.693692207
407811.219635934850693.054803327408605.924497068850984.576794073
#Sta/Elev= 30
9499.07387.336169716.76878.352679820.797 68.81659860.18459.019069971.06258.44695
 9994.1847.869539999.75747.7174110005.7447.76197 10019.756.9771710086.6560.15715
10307.8161.4268110318.1761.0948410328.5256.0087510368.8963.1084110409.2165.11439
10641.0161.8661910711.5663.5756510751.8767.8271910933.2471.9475611013.5267.92653
11208.7472.0787911310.0270.2625311745.5775.7174911815.8881.6657811837.1990.75294
11879.7997.8475611901.09104.736411911.75114.1691 11919.8117.400711976.64134.8771
#Mann= 3 , 0 , 0
9499.073  0.0535       09499.073  0.0535       011976.64  0.0535       0
#XS Ineff= 2 , 0
       0 9952.05         10407.7       0
Bank Sta=9499.073,11976.64
Exp/Cntr=0.3,0.1

Type RM Length L Ch R = 1 ,1956.605,728.963900,728.963900,728.963900
XS GIS Cut Line= 2
406293.203142881851210.307407483408385.217031777851266.731018603
#Sta/Elev= 30
9196.23788.809549328.08287.359669358.09382.503419438.12279.542589468.13380.07021
9538.15874.508999628.19172.28649 9708.2266.159869738.23158.806949768.24256.28839
9858.27554.067619938.30454.393549968.31553.013989998.32646.1643810028.3453.67913
10038.3454.2069410058.3552.5949210088.3654.2222910128.3752.54643 10198.456.41207
 10208.454.8173710298.4355.9776910418.4861.5512210538.5262.1215310738.5968.17262
10788.6167.3724310878.6570.8270811058.7169.9163511178.7571.1697411289.01  86.598
#Mann= 3 , 0 , 0
9196.237  0.0421       09196.237  0.0421       011289.01  0.0421       0
#XS Ineff= 2 , 0
       09825.646        10104.68       0
Bank Sta=9196.237,11289.01
Exp/Cntr=0.3,0.1