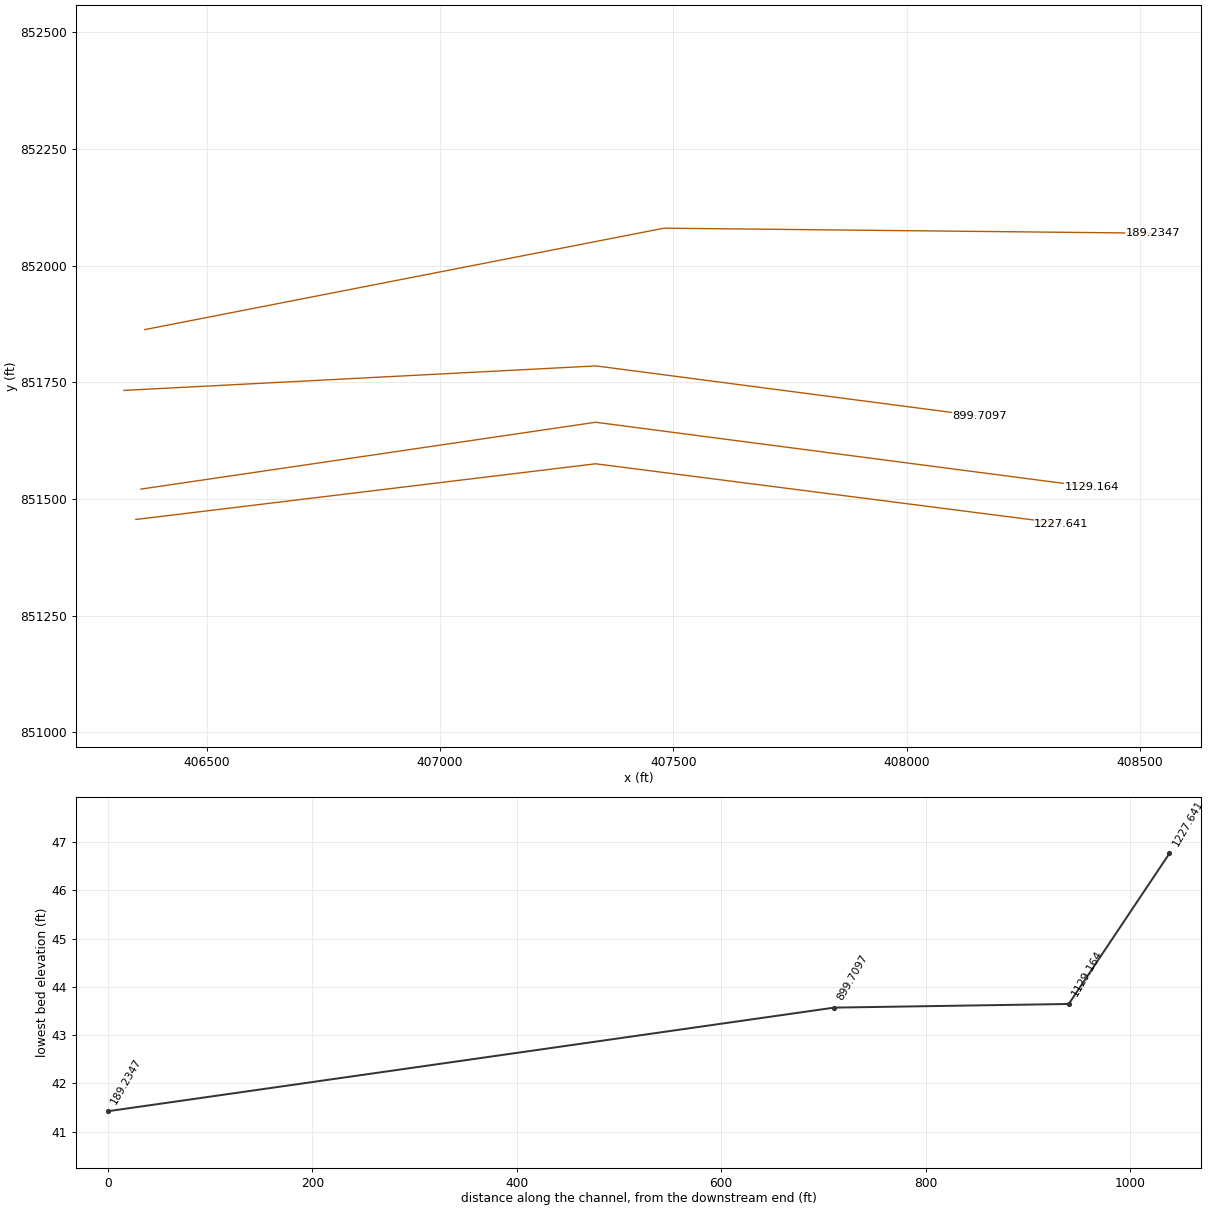
HEC-RAS study 7599_ras.prj: 7599

--- 7599_ras.g01 (geometry) --- (continued)

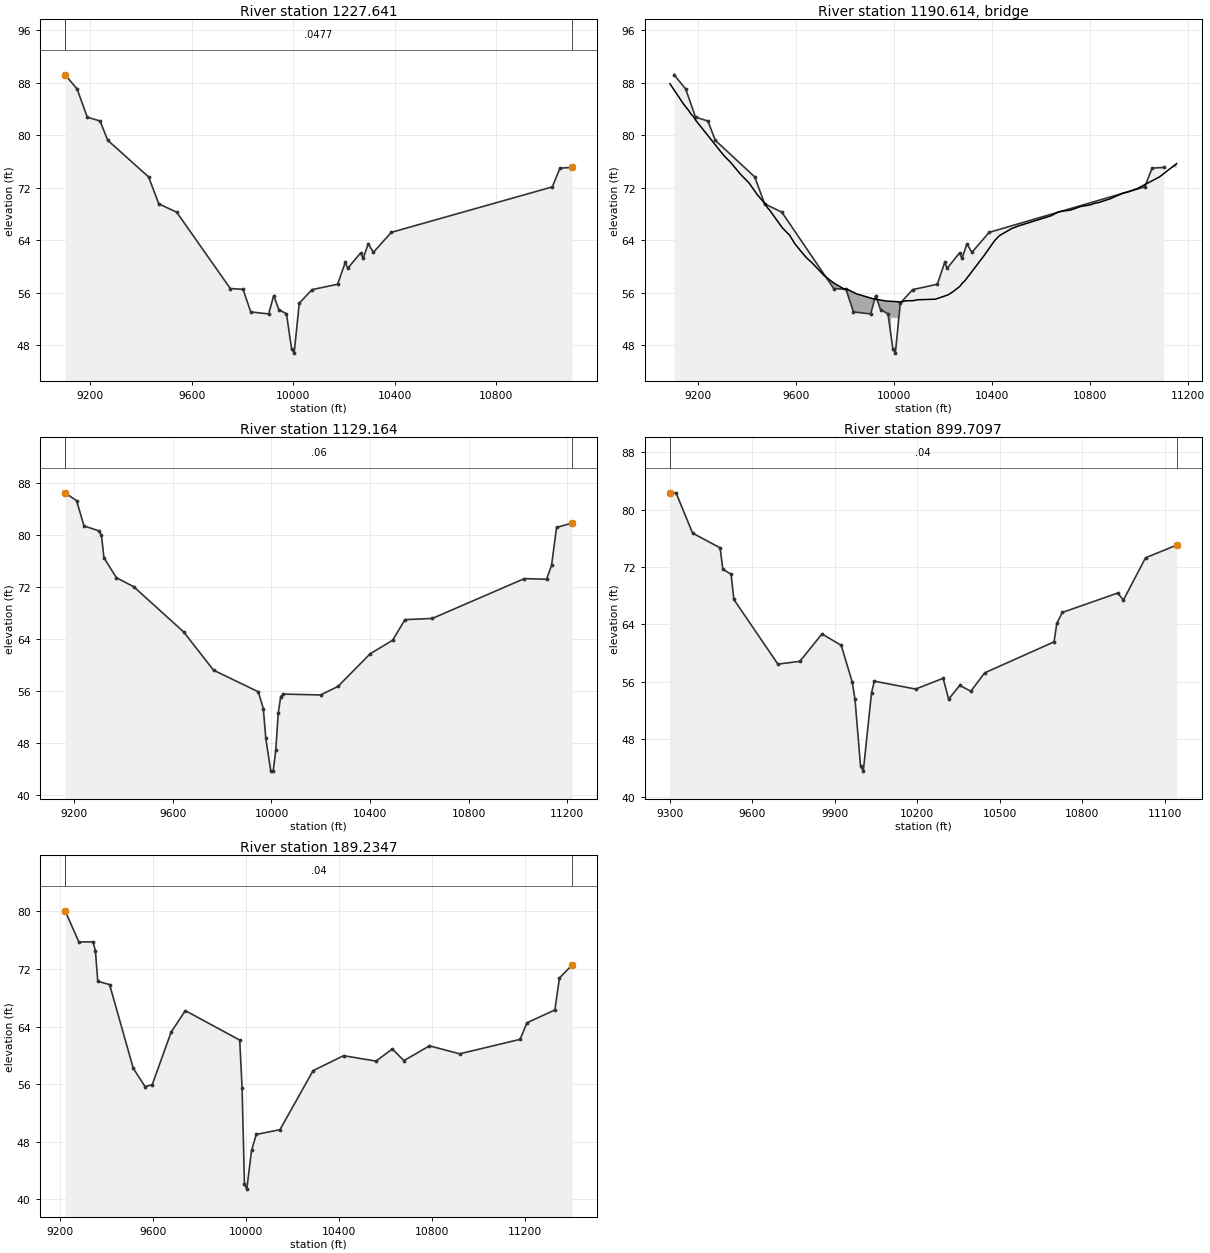
Type RM Length L Ch R = 1 ,1227.641,98.477500,98.477500,98.477500
XS GIS Cut Line= 3
406348.194933996851456.283690244407333.437989533 851575.64132911
408331.701878443851447.603134692
#Sta/Elev= 30
9100.63989.174829147.78687.020089188.07982.721399238.44482.141189268.66479.20016
9429.83373.619219470.12669.513859540.63868.242839752.17356.609629802.53956.48665
9832.75853.04724 9903.2752.736769923.41655.537699943.56253.391479973.78252.75068
9993.92847.39804   1000446.7654310024.1554.3763610074.5156.4437110175.3257.25847
10205.5660.5821410215.6459.7039810266.0562.0339210276.1361.19454 10296.363.42652
10316.4662.1224210387.0465.16592 11022.2 72.097611052.4474.9607411099.5375.06069
#Mann= 3 , 0 , 0
9100.639  0.0477       09100.639  0.0477       011099.53  0.0477       0
#XS Ineff= 2 , 0
       09952.591        10035.31       0
Bank Sta=9100.639,11099.53
Exp/Cntr=0.3,0.1

Type RM Length L Ch R = 3 ,1190.614,,,
BEGIN DESCRIPTION:
END DESCRIPTION:
Bridge Culvert--1,0,-1,-1, 0
Deck Dist Width WeirC Skew NumUp NumDn MinLoCord MaxHiCord MaxSubmerge Is_Ogee
37.263700,23.950100,2.6,0, 60, 60, , , 0.95, 0, 0,0,,
 9083.34 9139.06 9159.21 9169.29 9179.37 9189.45 9290.22 9310.38 9330.53 9370.84
 9406.51 9441.39 9471.62 9481.70 9491.77 9542.16 9572.39 9592.55 9622.78 9642.94
 9663.09 9713.48 9753.79 9794.10 9810.28 9844.49 9915.03 9965.58 9987.04 9987.04
10012.9610012.9610029.0310046.2910076.5910096.7410167.1910217.5110237.6410267.83
10277.8910287.9610368.4710408.7310428.8610479.1810509.3710640.2110670.4010720.72
10760.9810801.2310821.3610831.4310881.7510932.6910952.2010992.4511083.0311152.70
   87.83   84.72   83.78   83.21   82.82   82.22   77.50   76.61   75.87   74.06
   72.70   70.85   69.54   68.93   68.50   65.88   64.72   63.49   62.09   61.23
   60.55   58.58   57.41   56.56   56.44   55.81   55.03   54.71   54.66   54.66
   54.60   54.60   54.56   54.74   54.76   54.90   54.98   55.62   56.08   56.95
   57.46   57.79   61.74   63.88   64.67   65.75   66.18   67.70   68.30   68.58
   69.11   69.37   69.64   69.68   70.29   71.14   71.31   71.85   73.63   75.65
 -912.17 -915.28 -916.22 -916.79 -917.18 -917.78 -922.50 -923.39 -924.13 -925.94
 -927.30 -929.15 -930.46 -931.07 -931.50 -934.12 -935.28 -936.51 -937.91 -938.77
 -939.45 -941.42 -942.59 -943.44 -943.56 -944.19 -944.97 -945.29 -945.34   52.16
   52.10 -945.40 -945.44 -945.26 -945.24 -945.10 -945.02 -944.38 -943.92 -943.05
 -942.54 -942.21 -938.26 -936.12 -935.33 -934.25 -933.82 -932.30 -931.70 -931.42
 -930.89 -930.63 -930.36 -930.32 -929.71 -928.86 -928.69 -928.15 -926.37 -924.35
 9083.34 9139.06 9159.21 9169.29 9179.37 9189.45 9290.22 9310.38 9330.53 9370.84
 9406.51 9441.39 9471.62 9481.70 9491.77 9542.16 9572.39 9592.55 9622.78 9642.94
 9663.09 9713.48 9753.79 9794.10 9810.28 9844.49 9915.03 9965.58 9987.04 9987.04
10012.9610012.9610029.0310046.2910076.5910096.7410167.1910217.5110237.6410267.83
10277.8910287.9610368.4710408.7310428.8610479.1810509.3710640.2110670.4010720.72
10760.9810801.2310821.3610831.4310881.7510932.6910952.2010992.4511083.0311152.70
   87.83   84.72   83.78   83.21   82.82   82.22   77.50   76.61   75.87   74.06
   72.70   70.85   69.54   68.93   68.50   65.88   64.72   63.49   62.09   61.23
   60.55   58.58   57.41   56.56   56.44   55.81   55.03   54.71   54.66   54.66
   54.60   54.60   54.56   54.74   54.76   54.90   54.98   55.62   56.08   56.95
   57.46   57.79   61.74   63.88   64.67   65.75   66.18   67.70   68.30   68.58
   69.11   69.37   69.64   69.68   70.29   71.14   71.31   71.85   73.63   75.65
 -912.17 -915.28 -916.22 -916.79 -917.18 -917.78 -922.50 -923.39 -924.13 -925.94
 -927.30 -929.15 -930.46 -931.07 -931.50 -934.12 -935.28 -936.51 -937.91 -938.77
 -939.45 -941.42 -942.59 -943.44 -943.56 -944.19 -944.97 -945.29 -945.34   52.16
   52.10 -945.40 -945.44 -945.26 -945.24 -945.10 -945.02 -944.38 -943.92 -943.05
 -942.54 -942.21 -938.26 -936.12 -935.33 -934.25 -933.82 -932.30 -931.70 -931.42
 -930.89 -930.63 -930.36 -930.32 -929.71 -928.86 -928.69 -928.15 -926.37 -924.35
BR Coef=-1 , 0 , 0 ,, 0 ,,,0.8,0,1,0,
WSPro=,,,, 1 ,,,, 0 ,,,, 0 ,,,,-1 ,-1 ,-1 , 0 , 0 , 0 , 0 , 0
BC Design=,, 0 ,, 0 ,,,,,,

Type RM Length L Ch R = 1 ,1129.164,229.454300,229.454300,229.454300
XS GIS Cut Line= 3
406359.045628458851521.387856886407333.437989533851664.617023587
408396.806045115851525.728134677
#Sta/Elev= 30
9162.34686.422069208.794 85.21779239.11681.331279299.76180.573659309.86879.88935
9319.97676.427279370.51373.382319441.26571.973699643.41465.046889764.70459.16432
9946.63855.836449966.85353.263039976.96148.686159997.176 43.644510007.2843.73036
10017.3946.87742 10027.552.5544910037.6155.1140410047.7155.4883510199.2155.35471
 10269.856.6599910400.9161.6873210491.6763.76121 10542.166.9307410653.0367.11484
11026.1773.2317511116.9473.1423811137.1175.2956811157.28 81.099611219.6181.76356
#Mann= 3 , 0 , 0
9162.346    0.06       09162.346    0.06       011219.61    0.06       0
#XS Ineff= 2 , 0
       09937.432        10057.41       0
Bank Sta=9162.346,11219.61
Exp/Cntr=0.3,0.1

Type RM Length L Ch R = 1 ,899.7097,710.475000,710.475000,710.475000
XS GIS Cut Line= 3
406322.717031747851732.876851946407334.264462709851785.351809978
408157.181129366851677.712921068
#Sta/Elev= 30
9300.31182.281469322.62482.333849382.70476.729429482.83974.668259492.85271.69481
9522.89370.993319532.90667.478249693.12158.473869773.22958.869289853.33662.68002
9923.43161.089219963.48455.957779973.49853.553559993.52544.3010110003.5443.56915
10033.58 54.486510043.5956.1012410193.7955.0018110293.9356.4995110313.9653.60432
 10354.355.5039910394.6454.7048310445.0757.25833 10697.261.5750210707.2864.15309
10727.4565.6734210929.16 68.379110949.3367.3792111030.0173.2899511143.1475.04773
#Mann= 3 , 0 , 0
9300.311    0.04       09300.311    0.04       011143.14    0.04       0
#XS Ineff= 2 , 0
       09894.095        10181.93       0
Bank Sta=9300.311,11143.14
Exp/Cntr=0.3,0.1

Type RM Length L Ch R = 1 ,189.2347,0.000000,0.000000,0.000000
XS GIS Cut Line= 3
 406366.98786509851863.085185274407480.097796053852080.490698844
408528.446198434852069.682407483
#Sta/Elev= 30
 9221.1180.087439280.21875.759929341.35275.774549351.54174.53992 9361.7370.29843
9412.67569.837799514.56458.201279565.50955.663499596.07655.920399677.58763.23183
9738.721 66.22189973.06762.129429983.25655.452959993.44542.1019710003.6341.42134
10024.0146.8221210044.3949.0209810146.2849.6781610288.92 57.881710420.16 59.9582
10560.1759.2124310630.1760.8868110680.1759.2769510790.1861.3274910920.1860.22153
 11180.262.22684 11210.264.5300511330.2166.3159311350.2170.7702511403.6672.52801
#Mann= 3 , 0 , 0
 9221.11    0.04       0 9221.11    0.04       011403.66    0.04       0
#XS Ineff= 2 , 0
       09805.603        10220.08       0
Bank Sta=9221.11,11403.66
Exp/Cntr=0.3,0.1